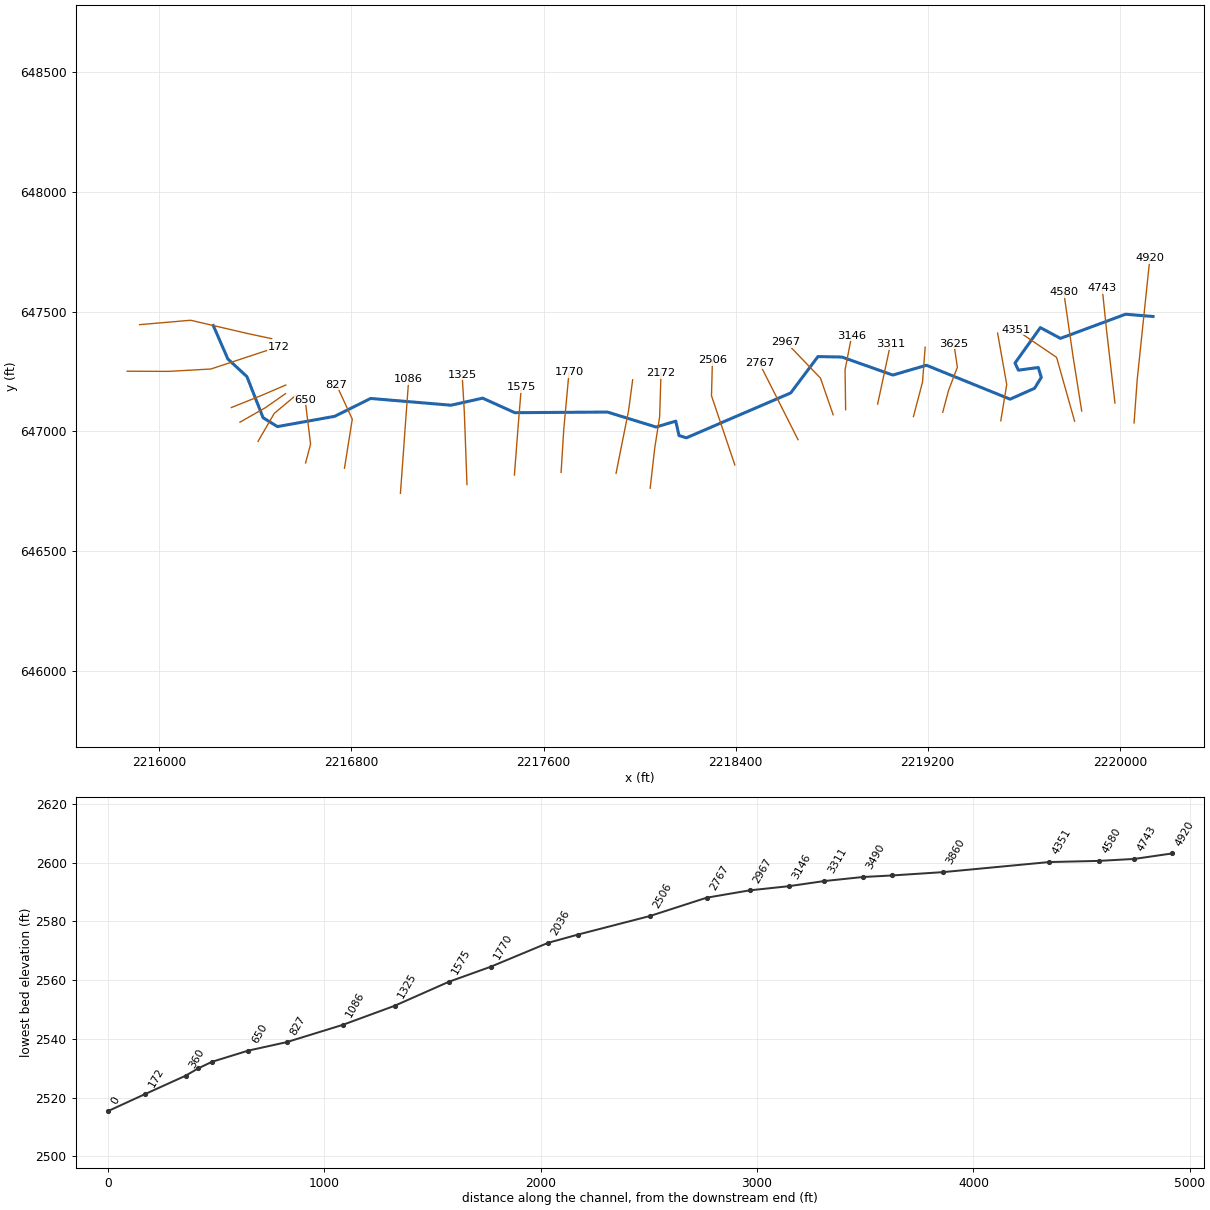
--- SUGARRN1.prj (project) ---

Proj Title=SUGARRN1
Current Plan=p01
Default Exp/Contr=0,0
English Units
Geom File=g01
Flow File=f01
Plan File=p01
BEGIN DESCRIPTION:
---------- MODELED AS PART OF WVEMD CTP PROGRAM, 2023----------
Stream Name: Sugar Run
Flood Zone:  AFH
Upshur County, WV
HEC-RAS Version: RAS 6.3
Vertical Datum: NAVD88
Projection: NAD 1983 StatePlane West Virginia S FIPS 4702 (US Feet)
Terrain: 1-meter LIDAR (FEMA Region III 3DEP collected 2016-2018)
Land Use: 2019 NLCD
Hydrologic Method:
WV SIR2010-5033 regression equations
Additional Model Notes:
Coincident peak with RFMIDDLERV; 2 shared XSs used due to parallel flow at DS extent
Model flows from Randolph County at US extent, flows from model SUGARN2; SUGARN2 uses 2 shared XSs at US extent
END DESCRIPTION:
DSS Export Rating Curves= 0
DSS Export Rating Curve Sorted= 0
DSS Export Volume Flow Curves= 0
DXF OffsetX= 0
DXF OffsetY= 0
DXF ScaleX= 0
DXF ScaleY= 0

--- SUGARRN1.p01 (plan) ---

Plan Title=Floodplain
Program Version=6.31
Short Identifier=Floodplain
Geom File=g01
Flow File=f01
Subcritical Flow
K Sum by GR= 0
Std Step Tol= 0.01
Critical Tol= 0.01
Num of Std Step Trials= 20
Max Error Tol= 0.3
Flow Tol Ratio= 0.001
Split Flow NTrial= 30
Split Flow Tol= 0.02
Split Flow Ratio= 0.02
Log Output Level= 0
Friction Slope Method= 1
Unsteady Friction Slope Method= 2
Unsteady Bridges Friction Slope Method= 1
Parabolic Critical Depth
Global Vel Dist= 0 , 0 , 0
Global Log Level= 0
CheckData=True
Encroach Param=-1 ,0,0, 0
Mapping Interval=1HOUR
Computation Time Step Use Courant=        0
Computation Time Step Use Time Series=    0
Computation Time Step Count To Double=0
Computation Time Step Max Doubling=0
Computation Time Step Max Halving=0
Computation Time Step Residence Courant=0
Run HTab= 0
Run UNet= 0
Run Sediment= 0
Run PostProcess= 0
Run WQNet= 0
Run RASMapper=-1
UNET Theta= 0
UNET Theta Warmup= 0
UNET ZTol= 0
UNET ZSATol= 0
UNET MxIter= 0
UNET Max Iter WO Improvement= 0
UNET MaxInSteps= 0
UNET DtIC= 0
UNET DtMin= 0
UNET MaxCRTS= 0
UNET WFStab= 0
UNET SFStab= 0
UNET WFX= 1
UNET SFX= 1
UNET Gravity=32.17405
UNET 1D Methodology=Finite Difference
UNET DSS MLevel= 1
UNET Pardiso=0
UNET DZMax Abort= 0
UNET Use Existing IB Tables= 0
UNET Froude Reduction=False
UNET Froude Limit= 0
UNET Froude Power= 0
UNET D1 Cores= 0
UNET WindReference=Eulerian
UNET WindDragFormulation=Hsu (1988)
UNET D2 Coriolis=0
UNET D2 Cores= 0
UNET D2 Theta= 1
UNET D2 Theta Warmup= 1
UNET D2 Z Tol= 0.01
UNET D2 Volume Tol= 0.01
UNET D2 Max Iterations= 20
UNET D2 Equation= 0
UNET D2 RampUpFraction=0.1
UNET D2 TimeSlices= 1
UNET D2 Turbulence Formulation=Non-Conservative (original)
UNET D2 Eddy Viscosity=0.3
UNET D2 Transverse Eddy Viscosity=0.1
UNET D2 Smagorinsky Mixing=0
UNET D2 BCVolumeCheck=0
UNET D2 Cores=0
UNET D2 SolverType=PARDISO (Direct)
UNET D2 Minimum Iterations= 3
UNET D2 Maximum Iterations= 30
UNET D2 Restart Number= 10
UNET D2 Relaxation Coeff=1.3
UNET D2 SOR Precondition Iterations= 10
UNET D2 ILUT Maximum Fill= 8
UNET D2 ILUT Tolerance=1E-08
UNET D2 Convergence Tolerance=0.00001
UNET D1D2 MaxIter= 0
UNET D1D2 ZTol=0.01
UNET D1D2 QTol=0.1
UNET D1D2 MinQTol=1
Write IC File= 0
Write IC File at Fixed DateTime=0
Write IC File at Sim End=0
Echo Input=False
Echo Parameters=False
Echo Output=False
Write Detailed= 0
HDF Write Warmup=0
HDF Write Time Slices=0
HDF Flush=0
HDF Compression= 1
HDF Chunk Size= 1
HDF Spatial Parts= 1
HDF Use Max Rows=0
HDF Fixed Rows= 1
Calibration Method= 0
Calibration Iterations= 20
Calibration Max Change=0.05
Calibration Tolerance=0.2
Calibration Maximum=1.5
Calibration Minimum=0.5
Calibration Optimization Method= 1
WQ AD Non Conservative
WQ ULTIMATE=-1
WQ Max Comp Step=1HOUR
WQ Output Interval=15MIN
WQ Output Selected Increments= 0
WQ Create Restart=0
WQ Fixed Restart=0
WQ System Summary=0
WQ Write To DSS=0
Sorting and Armoring Iterations= 10
XS Update Threshold= 0.02
Bed Roughness Predictor= 0
Hydraulics Update Threshold= 0.02
Energy Slope Method= 1
Volume Change Method= 1
Sediment Retention Method= 0
Sediment TS Multiplier= 1
Warm Up Method= 0
XS Weighting Method= 0
Number of US Weighted Cross Sections= 1
Number of DS Weighted Cross Sections= 1
Upstream XS Weight=0
Main XS Weight=1
Downstream XS Weight=0
Number of DS XS's Weighted with US Boundary= 1
Upstream Boundary Weight= 1
Weight of XSs Associated with US Boundary= 0
Number of US XS's Weighted with DS Boundary= 1
Downstream Boundary Weight= 0.5
Weight of XSs Associated with DS Boundary= 0.5
Percentile Method= 0
Sediment Output Level= 3
Mass or Volume Output= 0
Output Increment Type= 1
Profile and TS Output Increment= 1
Transport Output Increment 1
XS Output Flag= 0
XS Output Increment= 10
Read HDF5 Sediment Hotstart= 0
Sediment Hotstart Type= 0
Write Gradation File= 0
Read Gradation Hotstart= 0
Write HDF5 File= 1
Write Binary Output= 1
Write DSS Sediment File= 0
DSS Sediment Output Type= 1
SV Curve= 0
Specific Gage Flag= 0
Subcell Erosion Methods= 0
Subcell Deposition Methods= 0
Advection Scheme= 1
Matrix Solver= 0
Implicit Weighting Factor= 1
Maximum Outer Loop Convergence Iterations= 5
Convergence Maximum Absolute= 0.001
Convergence RMSE= 0.0001
Grain Fractions Max Abs Error= 0.001
Max Subgrid Regions= 1
Max Subgrid Length Scale= 3.402823E+38
Initial Layer Thickness= 3.402823E+38
Min Layer Thickness= 3.402823E+38
Max Layer Thickness= 3.402823E+38
Number of Layers= 5

--- SUGARRN1.f01 (steady flow) ---

Flow Title=Flows
Program Version=6.31
Number of Profiles= 1
Profile Names=01pct
River Rch & RM=SUGARRN1,Main            ,4920
     464
River Rch & RM=SUGARRN1,Main            ,0
    1100
Boundary for River Rch & Prof#=SUGARRN1,Main            , 1
Up Type= 0
Dn Type= 1
Dn Known WS=2520.32
DSS Import GetInterval= 0
DSS Import GetPeak= 0
DSS Import FillOption= 0

--- SUGARRN1.g01 (geometry) ---

Geom Title=Geometry
Program Version=6.31

River Reach=SUGARRN1        ,Main
Reach XY= 30
2220138.20873342647479.3539337072220023.82500002647488.780000016
2219752.68400002647387.9640000022219668.86700003647432.978000015
2219563.50100005647285.0020000192219577.49500003647255.356000006
2219660.51100002647266.4300000072219672.84500003647225.165999994
     2219644.743647179.4650000042219542.89800003647134.280000001
2219194.63600001647275.7590000032219054.41599999 647234.92400001
2218842.54000001647310.0699999932218742.78299998 647311.98800002
2218629.49099998647160.3780000062218194.92300004646972.998000011
2218164.16000001646982.240999997     2218150.682647042.479000002
2218068.58099999647018.0400000212217865.80600002647080.452999994
2217480.28599998 647077.84800002     2217346.361647138.487000003
2217214.55400001647109.0119999952216879.77100001647137.226999998
2216730.25000001647062.682000011     2216491.561647019.813999996
2216431.98099999647056.7300000192216364.73300003647228.170000017
2216285.15099999      647302.287 2216224.4552571647441.631174368

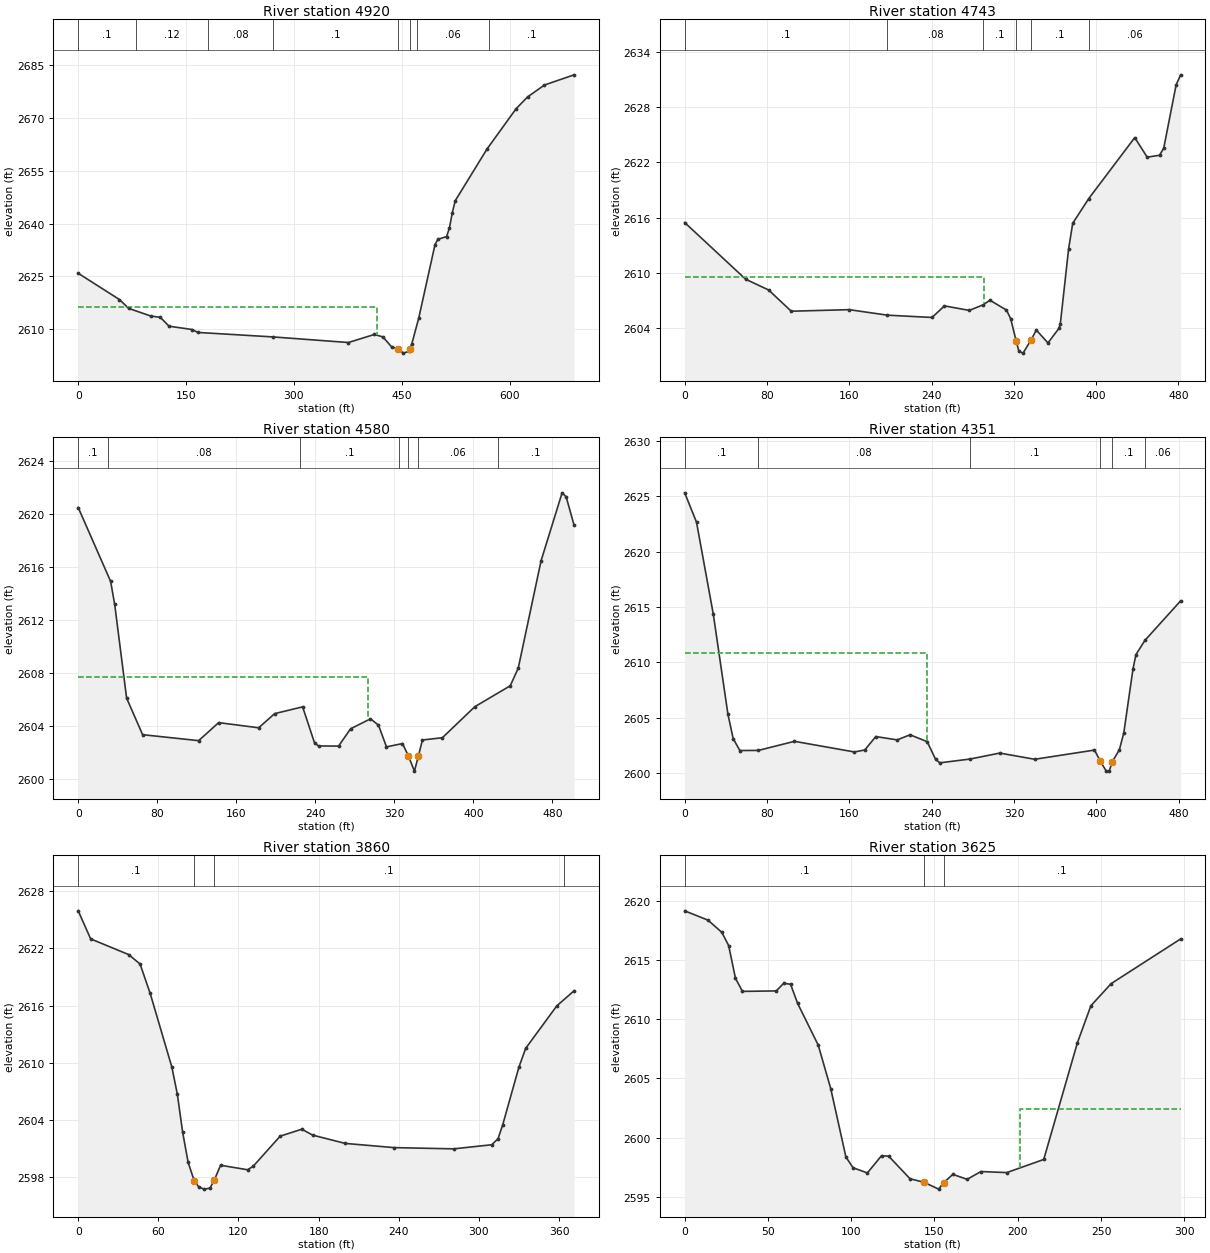
Type RM Length L Ch R = 1 ,4920    ,173,176.3,177.2
XS GIS Cut Line= 3
2220059.26647357647035.1758165062220072.30504016647215.709815493
2220125.01596288 647721.68526221
#Sta/Elev= 30
       0 2625.85    57.4 2618.37    70.2 2615.86   100.6 2613.71   114.3  2613.3
   126.3 2610.79   158.4 2609.85   166.4 2609.02     271 2607.74   375.8 2606.15
   411.8 2608.44   423.8 2607.74   435.8 2604.91   444.5 2604.42   452.2 2603.13
     460 2603.64   461.4 2604.43     464 2605.82   473.6 2613.12   496.2 2634.02
   500.2 2635.53   512.3 2636.29   516.3 2638.78   520.3 2643.15   524.3 2646.49
   568.3 2661.15   608.8 2672.64   624.9 2676.04   648.4 2679.43   689.7 2682.33
#Mann= 8 ,-1,0
       0      .1       0      80     .12       0     180     .08       0
     271      .1       0   444.5    .045       0   461.4      .1       0
     471     .06       0     571      .1       0
#XS Ineff= 2 , 0
       0414.8592 2616.33               0
Permanent Ineff=
       F       F
Bank Sta=444.5,461.4
XS Rating Curve= 0 ,0
Exp/Cntr(USF)=0,0
Exp/Cntr=0.3,0.1

Type RM Length L Ch R = 1 ,4743    ,162.5,163.6,163.5
XS GIS Cut Line= 3
2219979.69629634647118.2841097012219945.02584386 647419.17410802
2219926.45238717 647597.47929221
#Sta/Elev= 30
       0 2615.46    59.3 2609.29    81.6 2608.12   103.6 2605.81   159.9 2605.98
   197.1 2605.38   240.5 2605.13   252.6 2606.39   276.7  2605.9   290.5 2606.52
   296.8 2607.01   312.9 2605.93     317 2604.99   322.22602.615     325 2601.44
     329 2601.25   336.72602.666   341.9 2603.76   353.2 2602.36   363.8 2603.93
   365.2 2604.41   373.3  2612.6   377.3 2615.38   392.9 2618.07   437.6  2624.7
   449.7 2622.57   461.7 2622.78   465.8 2623.56   477.8 2630.42   482.2 2631.53
#Mann= 6 ,-1,0
       0      .1       0   197.1     .08       0   290.5      .1       0
   322.2    .045       0   336.7      .1       0   392.9     .06       0
#XS Ineff= 2 , 0
       0291.0197 2609.54               0
Permanent Ineff=
       F       F
Bank Sta=322.2,336.7
XS Rating Curve= 0 ,0
Exp/Cntr(USF)=0,0
Exp/Cntr=0.3,0.1

Type RM Length L Ch R = 1 ,4580    ,220.6,228.8,230.6
XS GIS Cut Line= 3
2219841.19898275647084.7676879952219805.99485295647306.824506755
2219766.27737317647581.236185222
#Sta/Elev= 30
       0 2620.47    32.8  2614.9    36.9 2613.18      49 2606.09    65.2 2603.33
   121.9 2602.88   142.2 2604.24   182.7 2603.85   198.9 2604.92   227.2 2605.43
   239.3  2602.7   243.4 2602.48   263.6 2602.47   275.7 2603.77   295.9 2604.53
     304 2604.05   312.1 2602.41   328.3 2602.66   334.2 2601.74   340.4 2600.58
   344.4 2601.72   348.5 2602.93   368.7  2603.1   401.5 2605.44   437.4 2607.02
   445.5 2608.35   468.6 2616.45   489.9 2621.58     494 2621.28   502.1 2619.12
#Mann= 7 ,-1,0
       0      .1       0      30     .08       0  224.83      .1       0
  324.83     .06       0   334.2    .045       0   344.4     .06       0
  424.83      .1       0
#XS Ineff= 2 , 0
          293.41 2607.69
Permanent Ineff=
       F       F
Bank Sta=334.2,344.4
XS Rating Curve= 0 ,0
Exp/Cntr(USF)=0,0
Exp/Cntr=0.3,0.1

Type RM Length L Ch R = 1 ,4351    ,494.1,490.6,475.4
XS GIS Cut Line= 3
2219811.55946057647042.4226832112219736.63785099647308.710331724
2219566.93589194647424.252091078
#Sta/Elev= 30
       0 2625.31    11.5 2622.66    27.8 2614.36      42 2605.34    47.1 2603.13
    53.6 2602.05    71.6 2602.06   106.7 2602.88   164.9 2601.92     175  2602.1
   185.7 2603.31   206.5 2603.01     219 2603.47   235.6 2602.85   243.9 2601.24
     248 2600.94   277.2 2601.28   306.2 2601.82   340.1 2601.26   398.2 2602.09
     404 2601.06   409.7 2600.19   412.6 2600.22   415.5 2601.04   422.4 2602.12
   426.7 2603.65   435.6  2609.4   438.5 2610.71   447.2 2611.99   481.9 2615.56
#Mann= 6 ,-1,0
       0      .1       0    71.6     .08       0   277.2      .1       0
     404    .045       0   415.5      .1       0   447.2     .06       0
#XS Ineff= 2 , 0
          235.49 2610.82
Permanent Ineff=
       F       F
Bank Sta=404,415.5
XS Rating Curve= 0 ,0
Exp/Cntr(USF)=0,0
Exp/Cntr=0.3,0.1

Type RM Length L Ch R = 1 ,3860    ,236,234.9,233.2
XS GIS Cut Line= 3
2219504.25797583647043.9803484062219528.90086669 647195.53864056
 2219490.8984599647409.922764362
#Sta/Elev= 30
       0 2625.92     9.3 2622.98    37.7 2621.34    46.3 2620.35    53.9 2617.26
    70.1 2609.55    74.2 2606.72    78.2 2602.71    82.3 2599.56    86.82597.657
    90.4 2596.96    94.4 2596.76    98.6 2596.86   101.82597.683   106.6 2599.26
   126.8 2598.79   130.9 2599.14   151.2 2602.31   167.4 2603.04   175.5 2602.42
   199.9 2601.55   236.5 2601.11   281.1 2600.98   309.6 2601.41   314.3 2602.04
   317.8 2603.49   329.9 2609.52     335 2611.51   358.3 2615.96   371.3 2617.55
#Mann= 4 ,-1,0
       0      .1       0    86.8    .045       0   101.8      .1       0
  363.55     .06       0
Bank Sta=86.8,101.8
XS Rating Curve= 0 ,0
Exp/Cntr(USF)=0,0
Exp/Cntr=0.3,0.1

Type RM Length L Ch R = 1 ,3625    ,133.9,135.5,139.7
XS GIS Cut Line= 4
2219262.45633438647079.6652830912219286.82842425647171.466821579
2219323.38655904647267.3303750432219308.76330512 647366.44354049
#Sta/Elev= 30
       0 2619.19      14  2618.4    22.3 2617.37    26.4 2616.25    30.5 2613.48
    34.7 2612.37      55 2612.41    59.5 2613.06    63.6 2612.97    67.8 2611.36
    80.2 2607.82    87.7 2604.14    96.8 2598.36   101.1 2597.44   109.7    2597
   118.2 2598.46   122.5 2598.42   135.3 2596.51   143.7 2596.21   152.5 2595.63
  155.49 2596.17     161 2596.88   169.6 2596.46   177.9 2597.12   193.4 2597.03
   215.6 2598.14   235.8 2608.01   243.9 2611.15   256.1 2613.03   297.8 2616.81
#Mann= 3 ,0,0
       0      .1       0   143.7    .045       0  155.49      .1       0
#XS Ineff= 2 , 0
                          201.63         2602.38
Permanent Ineff=
       F       F
Bank Sta=143.7,155.49
XS Rating Curve= 0 ,0
Exp/Cntr(USF)=0,0
Exp/Cntr=0.3,0.1

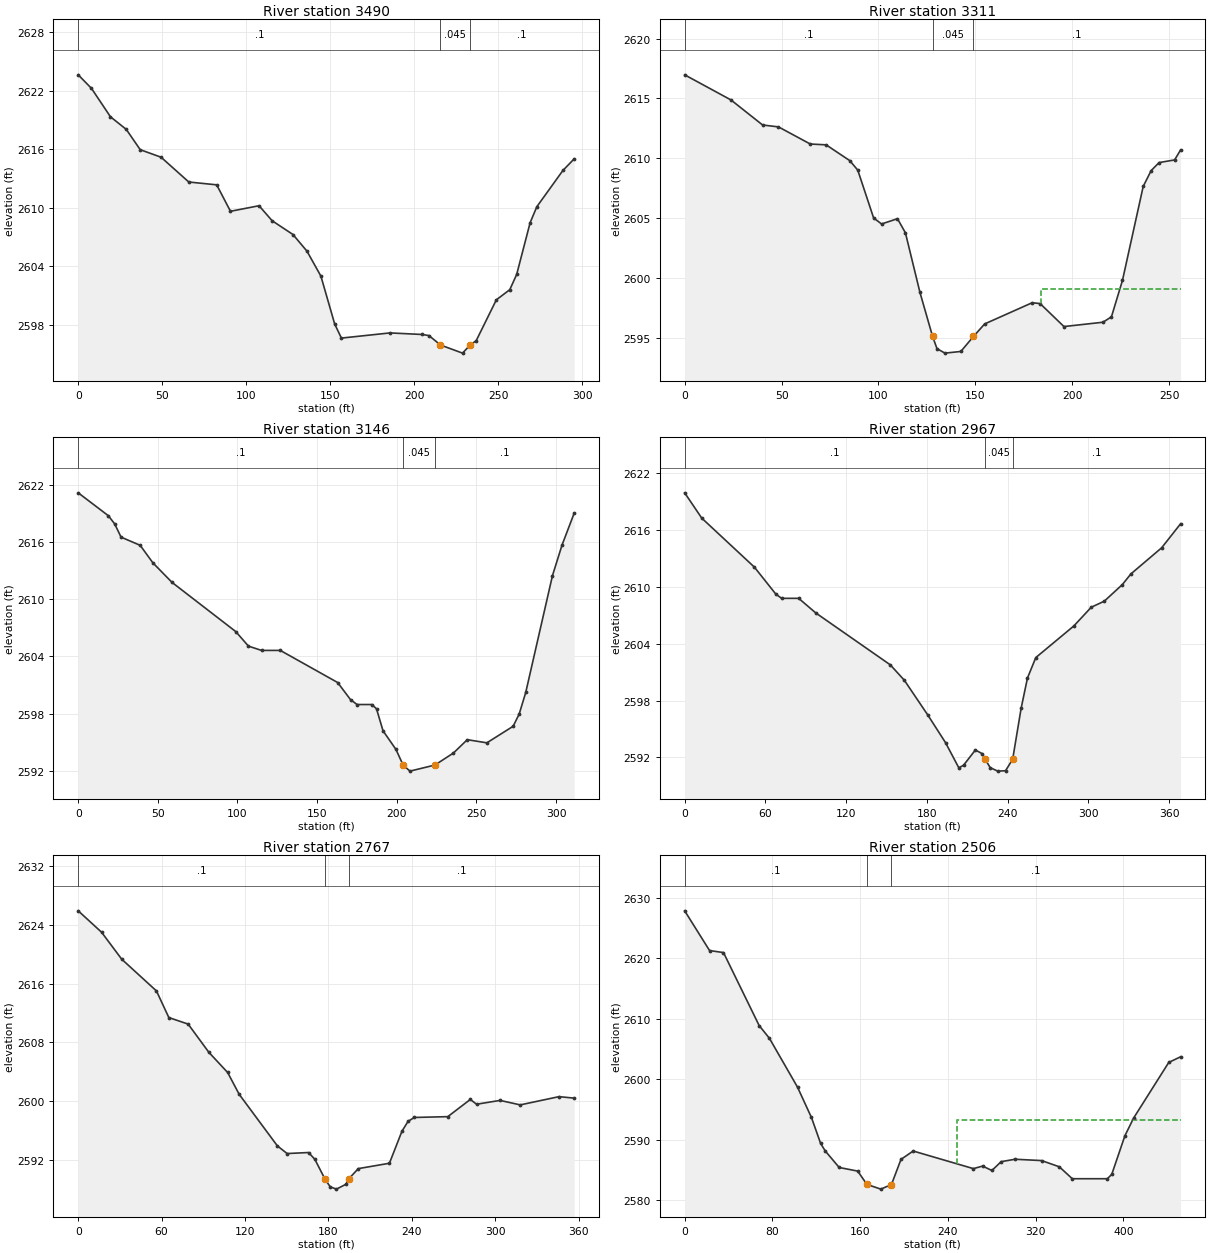
Type RM Length L Ch R = 1 ,3490    ,181.3,178.7,176.8
XS GIS Cut Line= 3
2219140.41535106647061.5216161932219178.32749085647205.948815386
2219189.15953079647351.278684575
#Sta/Elev= 30
       0 2623.61     7.9 2622.22    19.2 2619.31    28.6 2618.02    36.9 2615.94
    49.3 2615.17    65.8 2612.63    82.4 2612.34    90.6 2609.63   107.6  2610.2
   115.4 2608.66   127.8 2607.25   136.1 2605.55   144.4 2602.99   152.6 2598.09
   156.6 2596.64   185.5 2597.17   204.7 2597.01   208.7  2596.9  215.57 2595.93
   228.7  2595.1   233.2 2595.93   236.8 2596.37   248.8 2600.56   256.8  2601.6
   260.9 2603.16   268.9 2608.46   272.9  2610.1   288.4 2613.81   295.1    2615
#Mann= 3 ,0,0
       0      .1       0  215.57    .045       0   233.2      .1       0
Bank Sta=215.57,233.2
XS Rating Curve= 0 ,0
Exp/Cntr(USF)=0,0
Exp/Cntr=0.3,0.1

Type RM Length L Ch R = 1 ,3311    ,165.3,165.2,165.5
XS GIS Cut Line= 2
2218991.32324249647113.8374716412219044.94184019647364.057594244
#Sta/Elev= 30
       0 2616.97    23.9 2614.87    40.2 2612.78    48.4 2612.62    64.8 2611.19
      73 2611.12    85.2  2609.8    89.3 2609.01    97.5 2605.01   101.6 2604.51
   109.8 2604.95   113.9 2603.77   121.4 2598.79   127.92595.122   130.2 2594.09
   134.3 2593.72   142.5 2593.86     149 2595.11   154.8 2596.16   179.3 2597.93
   183.4 2597.86   195.7 2595.94   215.8  2596.3   220.2 2596.75   225.9  2599.8
   236.6 2607.65   240.7 2608.97   244.8 2609.64   252.8 2609.86   255.9  2610.7
#Mann= 3 ,0,0
       0      .1       0   127.9    .045       0     149      .1       0
#XS Ineff= 2 , 0
                          183.89         2599.08
Permanent Ineff=
       F       F
Bank Sta=127.9,149
XS Rating Curve= 0 ,0
Exp/Cntr(USF)=0,0
Exp/Cntr=0.3,0.1

Type RM Length L Ch R = 1 ,3146    ,169.9,179.4,188.4
XS GIS Cut Line= 3
2218858.08915123647090.2777847732218855.65194225647256.820398843
2218883.27364409647398.990923049
#Sta/Elev= 30
       0 2621.17    18.9 2618.77    22.9 2617.91    26.9 2616.52    38.9 2615.66
    46.9 2613.82    58.9 2611.77    98.9 2606.61   106.9 2605.08   115.1 2604.63
   126.9 2604.63   162.9 2601.26     171 2599.46   175.1 2598.95   184.4 2598.95
   187.3  2598.5   191.4 2596.19   199.5 2594.24     2042592.597   208.3 2591.96
     224  2592.6   235.6 2593.86   244.3 2595.26   256.6 2594.93   273.1 2596.67
   276.9 2597.96     281 2600.22   297.8 2612.49   303.8 2615.69   311.4 2619.03
#Mann= 3 ,0,0
       0      .1       0     204    .045       0     224      .1       0
Bank Sta=204,224
XS Rating Curve= 0 ,0
Exp/Cntr(USF)=0,0
Exp/Cntr=0.3,0.1

Type RM Length L Ch R = 1 ,2967    ,200.2,199.2,195.4
XS GIS Cut Line= 3
2218806.09535952647069.1553068912218753.28916482647221.887070038
2218610.30623762647371.369221203
#Sta/Elev= 30
       0 2619.92    12.7 2617.25    51.8 2612.08    67.7 2609.24      72 2608.79
    84.7 2608.79    97.4 2607.25   152.8 2601.77   163.2 2600.15   180.6 2596.49
   193.8 2593.57   203.7 2590.91   207.2 2591.18     216 2592.79   221.1  2592.4
  223.37 2591.79     227 2590.93   232.6 2590.56   238.4  2590.6   243.7 2591.81
     250 2597.19   254.7 2600.38   260.9 2602.54   289.2 2605.88   302.1 2607.85
   311.8 2608.49   325.2 2610.24   331.6 2611.37   354.4 2614.12   368.5 2616.66
#Mann= 3 ,0,0
       0      .1       0  223.37    .045       0   243.7      .1       0
Bank Sta=223.37,243.7
XS Rating Curve= 0 ,0
Exp/Cntr(USF)=0,0
Exp/Cntr=0.3,0.1

Type RM Length L Ch R = 1 ,2767    ,261.8,261,258.9
XS GIS Cut Line= 2
2218659.74519362646965.1927632992218499.27052785647283.913280038
#Sta/Elev= 30
       0 2625.91    16.8    2623    31.3 2619.33    56.3 2615.01    65.2 2611.39
    79.1  2610.5      94 2606.66   107.5 2603.92   115.8 2600.95   143.3 2593.93
   150.3 2592.89   165.7 2593.03   170.2 2592.12  177.47 2589.44   181.3 2588.36
   185.8 2588.05   192.6 2588.71   194.7 2589.46   201.5 2590.84   223.9 2591.57
   232.9 2595.92   237.3 2597.27   241.8  2597.8   265.9 2597.91   282.1 2600.25
   286.6  2599.6   303.5 2600.12     318 2599.51   345.9 2600.63   356.8 2600.43
#Mann= 3 ,0,0
       0      .1       0  177.47    .045       0   194.7      .1       0
Bank Sta=177.47,194.7
XS Rating Curve= 0 ,0
Exp/Cntr(USF)=0,0
Exp/Cntr=0.3,0.1

Type RM Length L Ch R = 1 ,2506    ,335.9,334.6,323.5
XS GIS Cut Line= 3
 2218396.6459885646859.6583824072218299.35822238647148.512780794
2218303.37008902647295.948879971
#Sta/Elev= 30
       0 2627.85    22.7 2621.28    35.4 2620.95    67.9 2608.89    77.3 2606.77
   102.9  2598.7   115.6 2593.69     124 2589.39   128.2 2588.15   140.9 2585.42
   157.8 2584.82   166.2 2582.62   178.9 2581.84  188.58  2582.6   197.3 2586.76
   208.4 2588.14   263.3 2585.23   271.7 2585.65   280.2 2584.92   288.6 2586.38
   301.3 2586.78   325.5 2586.56   341.7 2585.53   353.5 2583.56   385.5 2583.56
   389.5 2584.28   401.5 2590.67   409.5 2593.61   441.5 2602.79   452.3 2603.72
#Mann= 3 ,0,0
       0      .1       0   166.2    .045       0  188.58      .1       0
#XS Ineff= 2 , 0
       0                  248.73       0 2593.25
Permanent Ineff=
       F       F
Bank Sta=166.2,188.58
XS Rating Curve= 0 ,0
Exp/Cntr(USF)=0,0
Exp/Cntr=0.3,0.1

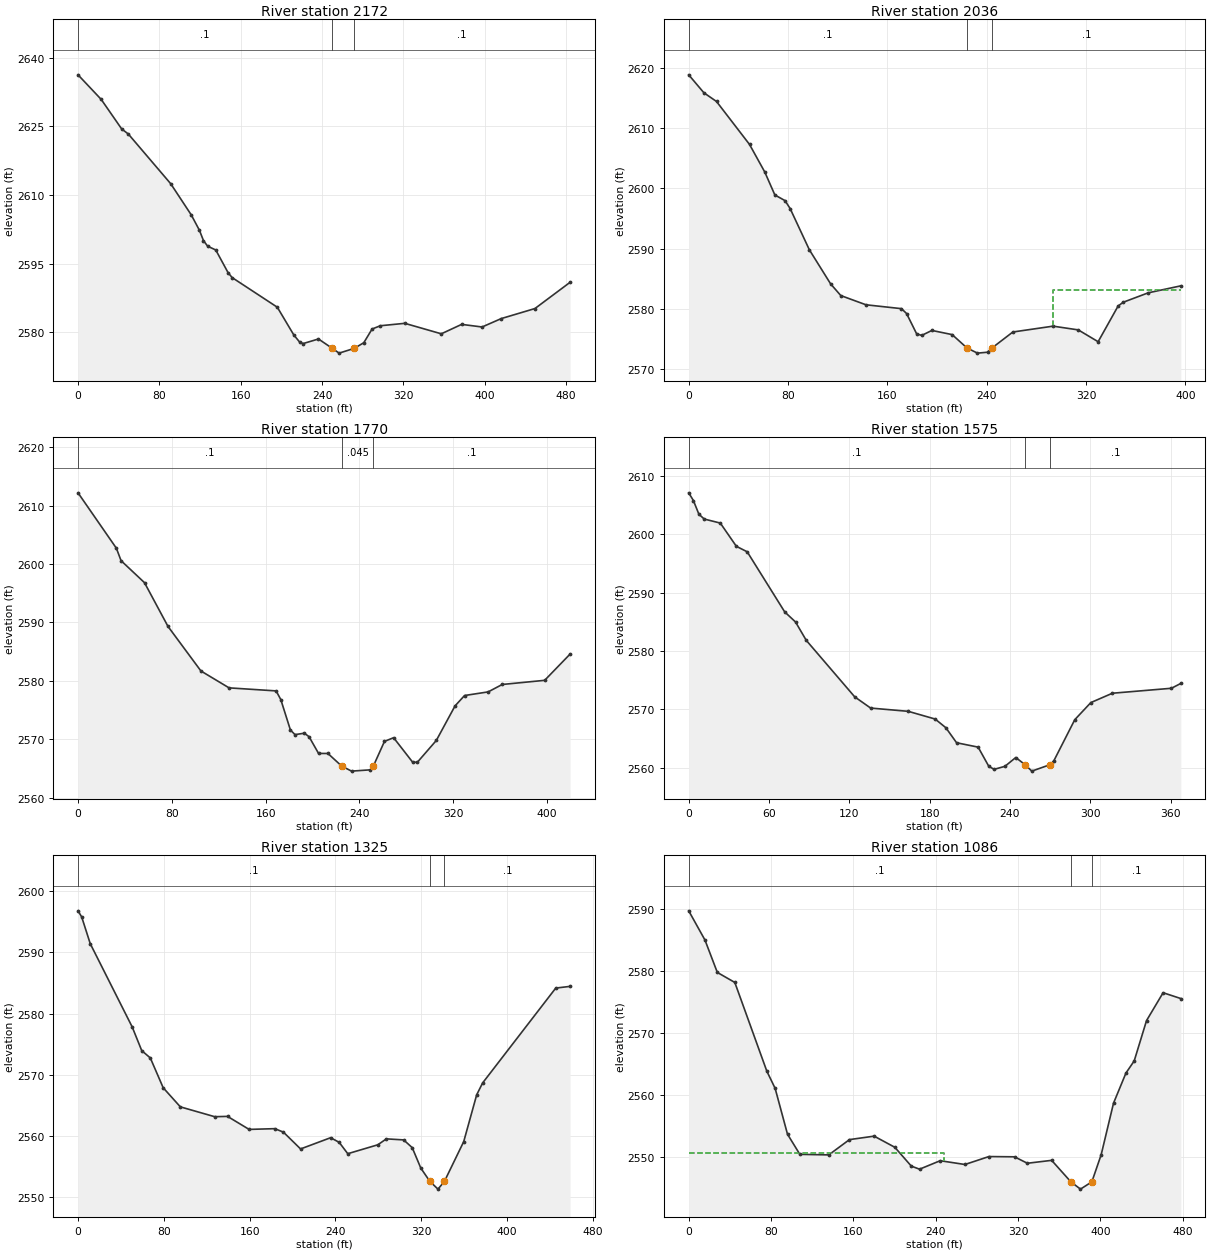
Type RM Length L Ch R = 1 ,2172    ,135.8,136.1,134.8
XS GIS Cut Line= 4
2218044.06812394646762.531586242 2218063.1244905646931.029985301
2218083.44987002647060.6537488532218089.20162369647243.754990221
#Sta/Elev= 30
       0 2636.28    22.8 2630.91    42.9 2624.47    49.5 2623.34    91.2 2612.48
   111.4 2605.67   119.4 2602.32   123.4 2600.06   127.5 2598.84   135.5 2598.01
   147.6 2593.05   151.6 2591.98     196 2585.51   212.2 2579.46   217.9 2577.91
   221.4 2577.57   236.5 2578.57  250.09 2576.52   256.8 2575.48   271.7 2576.52
   281.1 2577.76   289.2 2580.74   297.3 2581.46   321.4 2581.99   357.3  2579.7
   377.3 2581.76   397.4 2581.19   416.3 2583.03   449.4 2585.22     484 2590.96
#Mann= 3 ,0,0
       0      .1       0  250.09    .045       0   271.7      .1       0
Bank Sta=250.09,271.7
XS Rating Curve= 0 ,0
Exp/Cntr(USF)=0,0
Exp/Cntr=0.3,0.1

Type RM Length L Ch R = 1 ,2036    ,263.5,266.1,264.7
XS GIS Cut Line= 3
2217901.97481589 646825.089074162217954.12908226647086.863372698
 2217971.1795155647215.243105315
#Sta/Elev= 30
       0 2618.83    12.2 2615.86    22.4 2614.41      49 2607.29    61.3 2602.71
    69.4 2598.92    77.6 2597.98    81.7 2596.67    97.2 2589.83   114.3 2584.19
   122.5 2582.25   142.8 2580.72   171.4 2580.08   175.5 2579.27   183.6 2575.91
   187.7 2575.65   195.9 2576.47   212.2 2575.78  224.17 2573.56   232.6 2572.71
   240.7 2572.86   244.1 2573.53   261.1 2576.21   293.5 2577.18   313.8 2576.56
   329.8  2574.6   345.9 2580.52     350 2581.14   370.1  2582.7   396.4 2583.86
#Mann= 3 ,0,0
       0      .1       0  224.17    .045       0   244.1      .1       0
#XS Ineff= 2 , 0
                          293.31         2583.24
Permanent Ineff=
       F       F
Bank Sta=224.17,244.1
XS Rating Curve= 0 ,0
Exp/Cntr(USF)=0,0
Exp/Cntr=0.3,0.1

Type RM Length L Ch R = 1 ,1770    ,193.7,194.2,193.6
XS GIS Cut Line= 3
2217673.01362416646828.5808840172217684.04625743647006.105983026
2217706.11152398647246.817981681
#Sta/Elev= 30
       0 2612.18    32.7  2602.7    36.7 2600.57    56.7  2596.8    76.7 2589.32
   104.8 2581.69   128.8  2578.8   168.9 2578.28   172.9  2576.8   181.1 2571.59
     185  2570.8     193 2571.04     197 2570.44   205.1 2567.58   213.1 2567.57
  224.73 2565.43   233.2 2564.55   249.2 2564.77   251.9 2565.45   261.3 2569.64
   269.1 2570.27   285.4 2566.06   289.4 2566.08   305.5  2569.8   321.5 2575.72
   329.6 2577.49   349.7 2578.11   361.7 2579.38   397.9 2580.09   419.6 2584.59
#Mann= 3 ,0,0
       0      .1       0  224.73    .045       0   251.9      .1       0
Bank Sta=224.73,251.9
XS Rating Curve= 0 ,0
Exp/Cntr(USF)=0,0
Exp/Cntr=0.3,0.1

Type RM Length L Ch R = 1 ,1575    ,248.3,250.1,249.5
XS GIS Cut Line= 3
2217478.58612924646817.6485474112217493.93151916647018.041286292
2217507.47156908647184.132565365
#Sta/Elev= 30
       0 2607.07     3.5 2605.75     7.6 2603.41    11.6 2602.58    23.6 2601.89
    35.6 2597.91    43.7 2596.97    71.7 2586.68    79.8 2584.95    87.8 2581.81
     124 2572.13   135.9 2570.21     164 2569.65   184.1 2568.33   192.1 2566.84
   200.1 2564.27   216.2 2563.52   224.2 2560.22   228.2 2559.72   236.2 2560.23
   244.3 2561.74  251.33  2560.5   256.3 2559.41     2702560.522   272.8  2561.2
   288.4 2568.22   300.4 2571.15   316.5 2572.75   360.6  2573.6   367.6 2574.43
#Mann= 3 ,0,0
       0      .1       0  251.33    .045       0     270      .1       0
Bank Sta=251.33,270
XS Rating Curve= 0 ,0
Exp/Cntr(USF)=0,0
Exp/Cntr=0.3,0.1

Type RM Length L Ch R = 1 ,1325    ,239.7,239,238.3
XS GIS Cut Line= 3
2217281.10199368646777.8307709672217270.06936041647079.723735948
2217261.04266046647236.186535074
#Sta/Elev= 30
       0 2596.82     3.4 2595.83    11.4 2591.44    50.5 2577.81    59.4 2573.93
    67.4 2572.73    79.4 2567.85    95.4 2564.72   127.4 2563.11   139.4 2563.16
   159.5 2561.03   183.5 2561.15   191.5 2560.58   207.5 2557.83   235.5 2559.67
   243.5 2558.91   251.5 2557.05   279.5 2558.51   287.5 2559.48   303.6 2559.31
   311.6 2558.04   319.6 2554.69     328 2552.53   335.6 2551.25  341.59 2552.51
   359.6 2559.03   371.7  2566.7   377.2 2568.63   445.4 2584.17   458.8 2584.45
#Mann= 3 ,0,0
       0      .1       0     328    .045       0  341.59      .1       0
Bank Sta=328,341.59
XS Rating Curve= 0 ,0
Exp/Cntr(USF)=0,0
Exp/Cntr=0.3,0.1

Type RM Length L Ch R = 1 ,1086    ,253.7,259.6,262.9
XS GIS Cut Line= 3
2217004.01216034646741.4267958612217026.30030836647051.232053391
2217038.55878978647218.393163569
#Sta/Elev= 30
       0 2589.74    15.8 2585.02    27.8 2579.79    44.8 2578.17    75.9 2563.84
      84 2561.05      96 2553.65     108  2550.4   136.1 2550.31   156.2 2552.78
   180.2 2553.34   200.3 2551.54   216.3  2548.5   224.3    2548   244.4 2549.37
   268.4 2548.76   291.7 2550.04   316.6    2550   329.1 2548.96   352.7 2549.43
   371.3 2545.97   380.7 2544.78  391.76 2545.96   400.8 2550.33   412.8 2558.66
   424.9 2563.54   432.9 2565.49   444.9 2572.01     461 2576.51   478.2 2575.57
#Mann= 3 ,0,0
       0      .1       0   371.3    .045       0  391.76      .1       0
#XS Ineff= 2 , 0
       0  247.85 2550.65               0
Permanent Ineff=
       F       F
Bank Sta=371.3,391.76
XS Rating Curve= 0 ,0
Exp/Cntr(USF)=0,0
Exp/Cntr=0.3,0.1

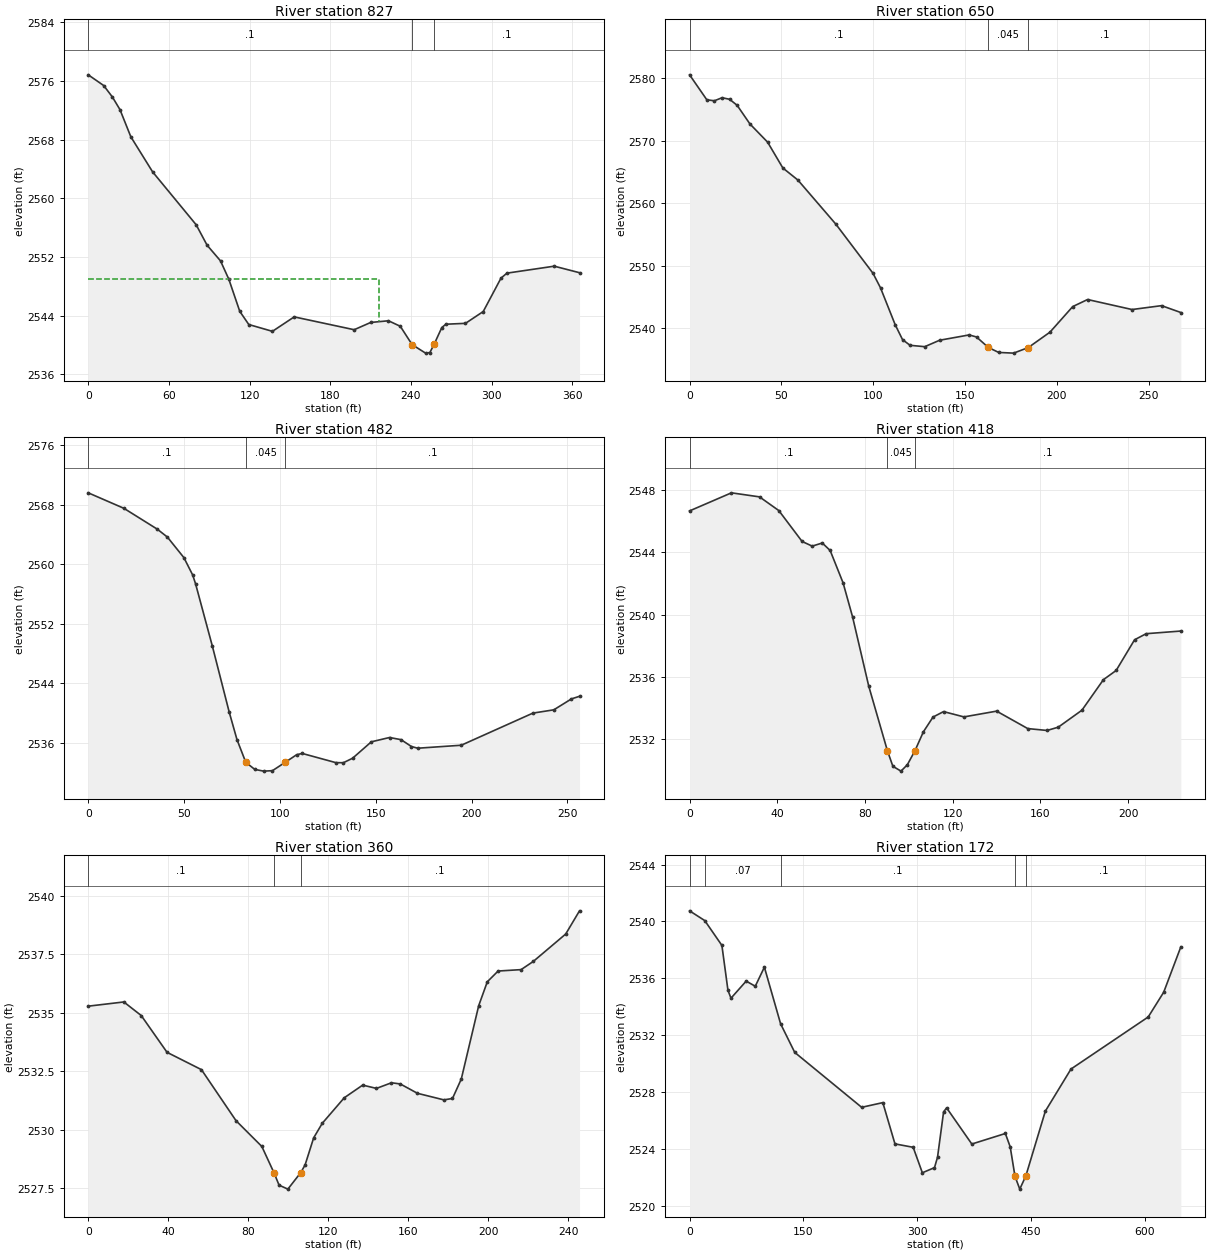
Type RM Length L Ch R = 1 ,827     ,179.7,176.3,174
XS GIS Cut Line= 3
2216770.89051432646845.8492458132216803.38663413647050.755334669
 2216737.4917245647194.279863868
#Sta/Elev= 30
       0 2576.82    11.5 2575.36      18 2573.79    23.6 2572.08    31.7 2568.37
    47.9 2563.59    80.3 2556.38    88.4  2553.6    98.4 2551.46   104.6 2548.95
   112.7 2544.59   119.4 2542.79     137 2541.86   153.2 2543.83   197.8 2542.08
   210.1 2543.07   223.3  2543.3   232.1 2542.55   240.9 2540.05   250.9 2538.89
   254.1 2538.97  257.22 2540.08     263 2542.38     266 2542.83   280.6 2542.95
   293.8 2544.56     307 2549.11   311.4 2549.79   346.6 2550.74   365.4 2549.85
#Mann= 3 ,0,0
       0      .1       0   240.9    .045       0  257.22      .1       0
#XS Ineff= 2 , 0
       0  216.34 2548.97               0
Permanent Ineff=
       F       F
Bank Sta=240.9,257.22
XS Rating Curve= 0 ,0
Exp/Cntr(USF)=0,0
Exp/Cntr=0.3,0.1

Type RM Length L Ch R = 1 ,650     ,174.3,168.7,161
XS GIS Cut Line= 3
2216609.00385309 646868.093918192216629.76526298646946.626207752
 2216607.1985131647131.673556719
#Sta/Elev= 30
       0 2580.52     9.4 2576.53    13.5 2576.37    17.7 2576.86    21.8 2576.61
    25.9 2575.65    32.9 2572.66    42.5 2569.76    50.8 2565.63      59  2563.7
    79.7 2556.64    99.9  2548.8     104 2546.47     112 2540.57     116 2538.19
   120.1 2537.28   128.1 2537.06   136.2 2538.09   152.3 2538.94   156.3 2538.61
  162.75 2536.93   168.4 2536.14   176.5 2536.03   184.5 2536.92   196.3 2539.38
   208.7 2543.47   216.8  2544.6     241    2543   257.1 2543.62   267.6 2542.52
#Mann= 3 ,0,0
       0      .1       0  162.75    .045       0   184.5      .1       0
Bank Sta=162.75,184.5
XS Rating Curve= 0 ,0
Exp/Cntr(USF)=0,0
Exp/Cntr=0.3,0.1

Type RM Length L Ch R = 1 ,482     ,68.2,63.9,58.1
XS GIS Cut Line= 3
2216410.87290309646958.005756047  2216478.651685647075.138019933
2216571.43623112 647152.78749824
#Sta/Elev= 30
       0 2569.61    18.6 2567.53      36 2564.73    41.3 2563.66    49.9  2560.9
    54.5 2558.56      56 2557.38    64.8 2548.96    73.5 2540.18    77.6 2536.44
    82.2 2533.38    86.9 2532.43    91.5  2532.2    96.1 2532.26   102.8 2533.39
   108.7  2534.4   111.6 2534.58   129.2 2533.34   133.1 2533.33   137.9 2533.93
   147.7 2536.14   157.2 2536.72   163.2 2536.43   168.6 2535.51   171.9 2535.28
   194.6 2535.68     232    2540   242.9 2540.44   252.1 2541.91   256.3 2542.26
#Mann= 3 ,0,0
       0      .1       0    82.2    .045       0   102.8      .1       0
Bank Sta=82.2,102.8
XS Rating Curve= 0 ,0
Exp/Cntr(USF)=0,0
Exp/Cntr=0.3,0.1

Type RM Length L Ch R = 1 ,418     ,58.5,57.8,56.7
XS GIS Cut Line= 3
2216335.60975297647038.2929868252216441.62695467647098.737183269
2216525.09751167647157.262516333
#Sta/Elev= 30
       0 2546.65    19.1 2547.81    31.9 2547.55    40.7 2546.67    51.3 2544.69
    55.9 2544.39    60.5 2544.59    64.1 2544.11      70 2542.03    74.3 2539.86
    81.7  2535.4    90.2 2531.26    92.7 2530.26    96.4 2529.95    99.3 2530.36
   102.8 2531.27   106.6 2532.47     111 2533.42   115.8 2533.77   125.1 2533.43
     140  2533.8   154.2 2532.68     163 2532.56   168.1 2532.77   178.9 2533.86
   188.7 2535.82   194.5 2536.41   202.9 2538.38   208.2 2538.77     224 2538.94
#Mann= 3 ,0,0
       0      .1       0    90.2    .045       0   102.8      .1       0
Bank Sta=90.2,102.8
XS Rating Curve= 0 ,0
Exp/Cntr(USF)=0,0
Exp/Cntr=0.3,0.1

Type RM Length L Ch R = 1 ,360     ,188.3,188,187
XS GIS Cut Line= 3
2216299.63106461647099.216899114 2216424.8369001647149.587062817
 2216526.5366592647193.241204693
#Sta/Elev= 30
       0 2535.28    17.8 2535.46    26.5 2534.88    39.4 2533.31    56.6 2532.57
    73.9 2530.39    86.8 2529.29    92.92528.161    95.4 2527.64    99.8 2527.47
  106.19 2528.17   108.4  2528.5   112.7 2529.66     117 2530.28     128 2531.37
   137.2 2531.91   144.1 2531.77   151.6 2532.01     156 2531.96   164.6 2531.56
   177.8 2531.28   182.1 2531.34   186.5 2532.17   195.2  2535.3   199.5 2536.32
   204.9 2536.78   216.4 2536.84   222.5 2537.19   238.7 2538.36   245.6 2539.35
#Mann= 3 ,0,0
       0      .1       0    92.9    .045       0  106.19      .1       0
Bank Sta=92.9,106.19
XS Rating Curve= 0 ,0
Exp/Cntr(USF)=0,0
Exp/Cntr=0.3,0.1

Type RM Length L Ch R = 1 ,172     ,182.2,171.8,160.3
XS GIS Cut Line= 4
 2215865.5930012647250.9694137682216037.34035409647250.213802524
2216214.57194918647260.096605225 2216497.6669864647354.007934263
#Sta/Elev= 30
       0 2540.75      202540.065    42.6 2538.32    50.6 2535.16    54.6 2534.61
    74.6 2535.81    86.6 2535.45    98.6 2536.79     1202532.807   138.6  2530.8
   226.8 2526.94   254.7 2527.27   270.7 2524.37   294.7 2524.13   306.8 2522.34
   322.8  2522.7   326.8 2523.43   334.8 2526.62   338.8  2526.9     372 2524.36
   416.2  2525.1   422.6 2524.16   428.9 2522.09   435.2 2521.19   443.2 2522.12
   468.9 2526.67   502.7 2529.63   604.5 2533.29   624.9 2535.03   647.5 2538.22
#Mann= 5 ,-1,0
       0     .05       0      20     .07       0     120      .1       0
   428.9    .045       0   443.2      .1       0
Bank Sta=428.9,443.2
XS Rating Curve= 0 ,0
Exp/Cntr=0.3,0.1

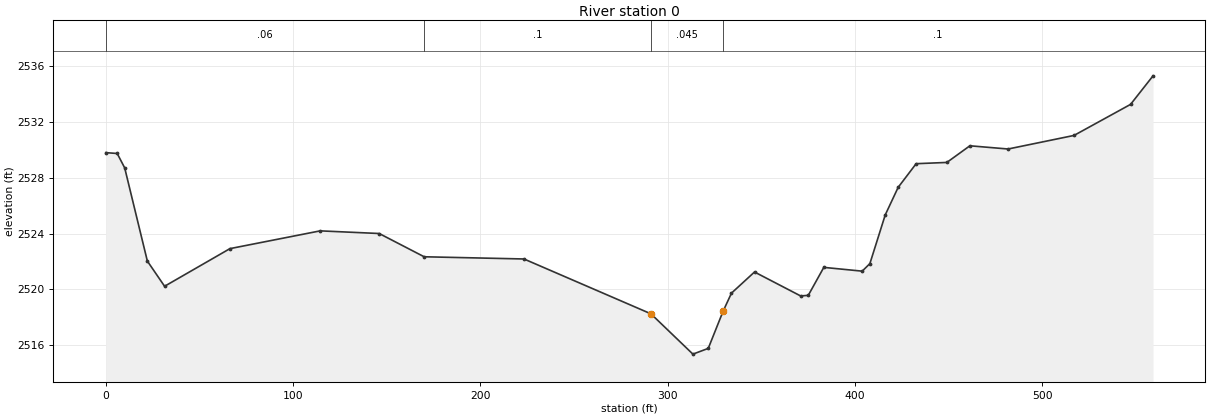
Type RM Length L Ch R = 1 ,0       ,207.2,229,247.5
XS GIS Cut Line= 4
2215918.07617905647445.2750020842216130.30045422647463.621541622
2216365.29154064647408.7170821772216467.77986494647386.755298399
#Sta/Elev= 30
       0 2529.78     6.1 2529.72    10.1 2528.69    22.2 2522.03    31.4 2520.23
    66.3 2522.92   114.5 2524.19     146    2524     1702522.338   223.3 2522.18
   291.1 2518.26   313.5 2515.38   321.7 2515.79   329.6 2518.44   334.1 2519.74
   346.4 2521.25     371 2519.54   375.1 2519.58   383.4 2521.58   403.9 2521.31
     408 2521.85   416.2 2525.33   423.1  2527.3   432.7 2528.99   449.1 2529.08
   461.4 2530.27   481.8 2530.04     517 2531.01   547.2 2533.23   559.2 2535.27
#Mann= 4 ,-1,0
       0     .06       0     170      .1       0   291.1    .045       0
   329.6      .1       0
Bank Sta=291.1,329.6
XS Rating Curve= 0 ,0
Exp/Cntr=0.3,0.1
LCMann Table=0

Chan Stop Cuts=-1
Use User Specified Reach Order=0
Composite Channel Slope=5